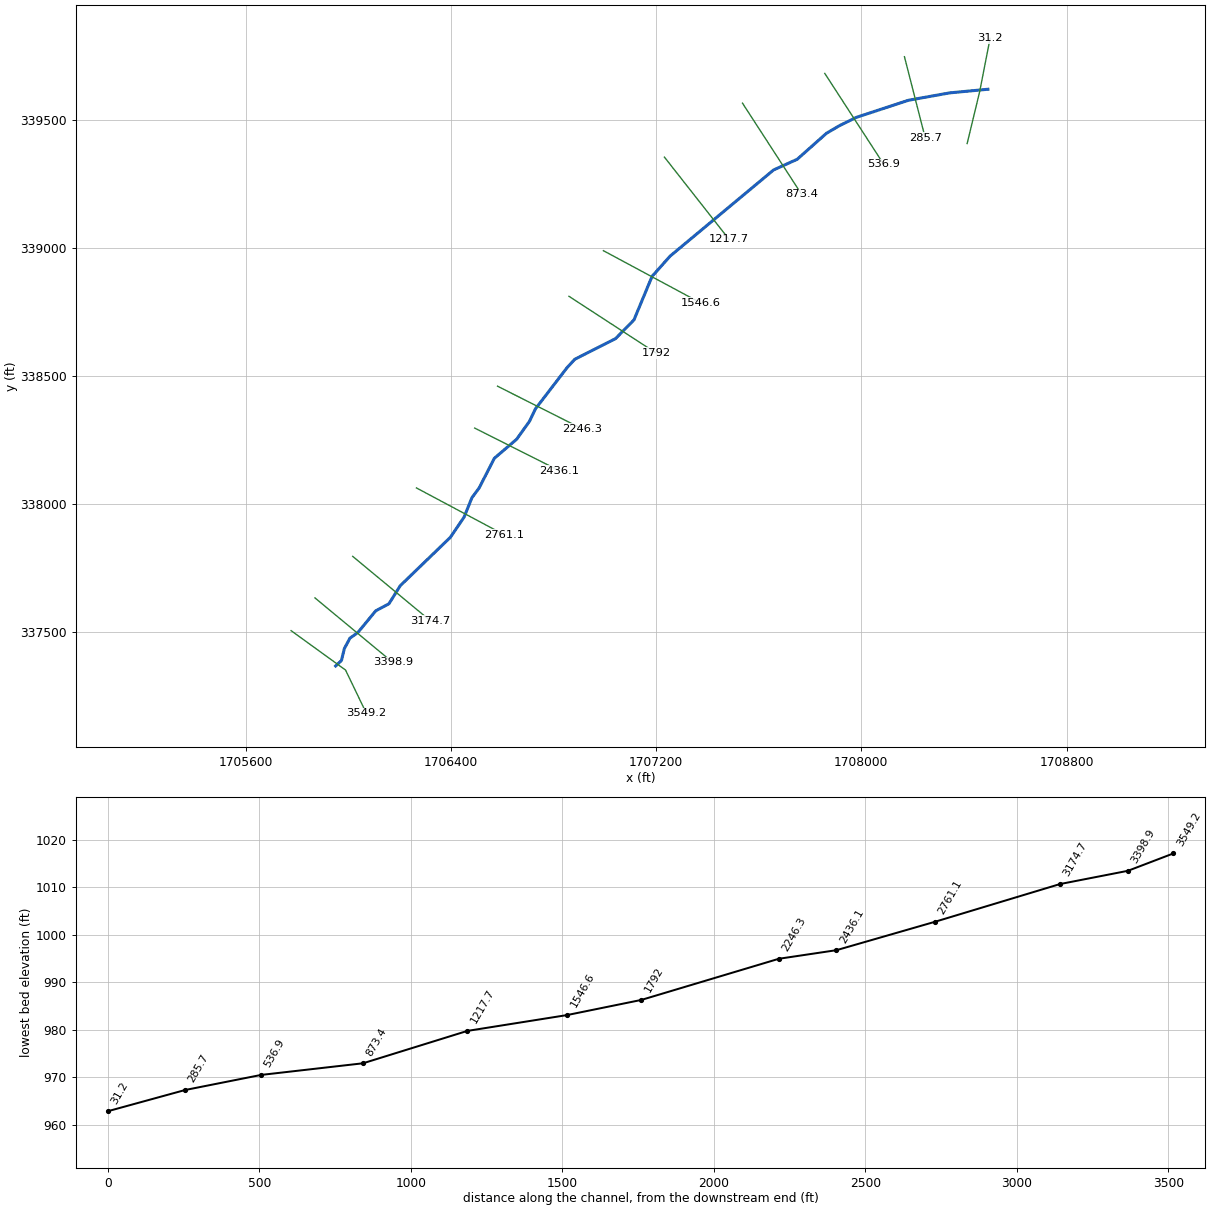
--- CRADCKBRCH.prj (project) ---

Proj Title=CRADCKBRCH
Current Plan=p01
Default Exp/Contr=0,0
English Units
Geom File=g01
Flow File=f01
Plan File=p01
BEGIN DESCRIPTION:
END DESCRIPTION:
DSS Export Rating Curves= 0
DSS Export Rating Curve Sorted= 0
DSS Export Volume Flow Curves= 0
DXF OffsetX= 0
DXF OffsetY= 0
DXF ScaleX= 0
DXF ScaleY= 0

--- CRADCKBRCH.p01 (plan) ---

Plan Title=Floodplain
Program Version=4.00
Geom File=g01
Flow File=f01
K Sum by GR=0
Std Step Tol=0.01
Critical Tol=0.01
Num of Std Step Trials=20
Max Error Tol=0.3
Flow Tol Ratio=0.001
Split Flow NTrial=30
Split Flow Tol=0.02
Split Flow Ratio=0.02
Log Output Level=0
Friction Slope Method=1
Unsteady Friction Slope Method=2
Unsteady Bridges Friction Slope Method=1
Global Log Level=0
CheckData=False
Run HTab=0
Run UNet=0
Run PostProcess=0
UNET Theta=0
UNET Theta Warmup=0
UNET ZTol=0
UNET ZSATol=0
UNET MxIter=0
UNET MaxInSteps=0
UNET DtIC=0
UNET DtMin=0
UNET MaxCRTS=0
UNET WFStab=0
UNET SFStab=0
UNET WFX=0
UNET SFX=0
UNET DSS MLevel=0
UNET DZMax Abort=0
UNET Convert EG Bridges=0
UNET Use Existing IB Tables=0
UNET Froude Limit=0
UNET Froude Power=0
Write IC File=0
Echo Input=False
Echo Output=False
Write Detailed=0

--- CRADCKBRCH.f01 (steady flow) ---

Flow Title=NFF Regression Equation
Program Version=4.00
Number of Profiles=1
Profile Names=P100yr
River Rch & RM=CRADCKBRCH,Main      ,3549.2
941.8351
River Rch & RM=CRADCKBRCH,Main      ,1217.7
976.4719
River Rch & RM=CRADCKBRCH,Main      ,873.4
1196.674
River Rch & RM=CRADCKBRCH,Main      ,285.7
1212.186
Boundary for River Rch & Prof#=CRADCKBRCH,Main      ,1
Up Type=0
Dn Type=3
Dn Slope=0.012506

--- CRADCKBRCH.g01 (geometry) ---

Geom Title=USGS 10m DEM
Program Version=4.10

River Reach=CRADCKBRCH      ,Main
Reach XY= 30
     1705951.056       337366.12     1705973.731      337387.535
     1705985.069      337434.145     1706006.485      337474.456
     1706037.978      337497.131     1706107.263      337581.533
     1706158.911      337609.247     1706203.002      337679.792
      1706398.26      337868.751     1706451.557      337947.377
     1706482.142      338023.228     1706510.375      338061.489
     1706569.582      338177.384     1706656.504      338251.708
     1706706.893      338322.252     1706729.568      338370.122
     1706853.021      338531.367     1706883.254       338564.12
      1707041.98      338644.743     1707113.784      338717.807
     1707184.329       338887.87     1707254.874      338967.233
     1707657.987       339303.58     1707749.947      339345.151
     1707864.582      339447.189     1707916.231      339477.422
     1707980.477      339508.915     1708183.293      339575.681
     1708344.538      339604.655     1708493.152      339618.716

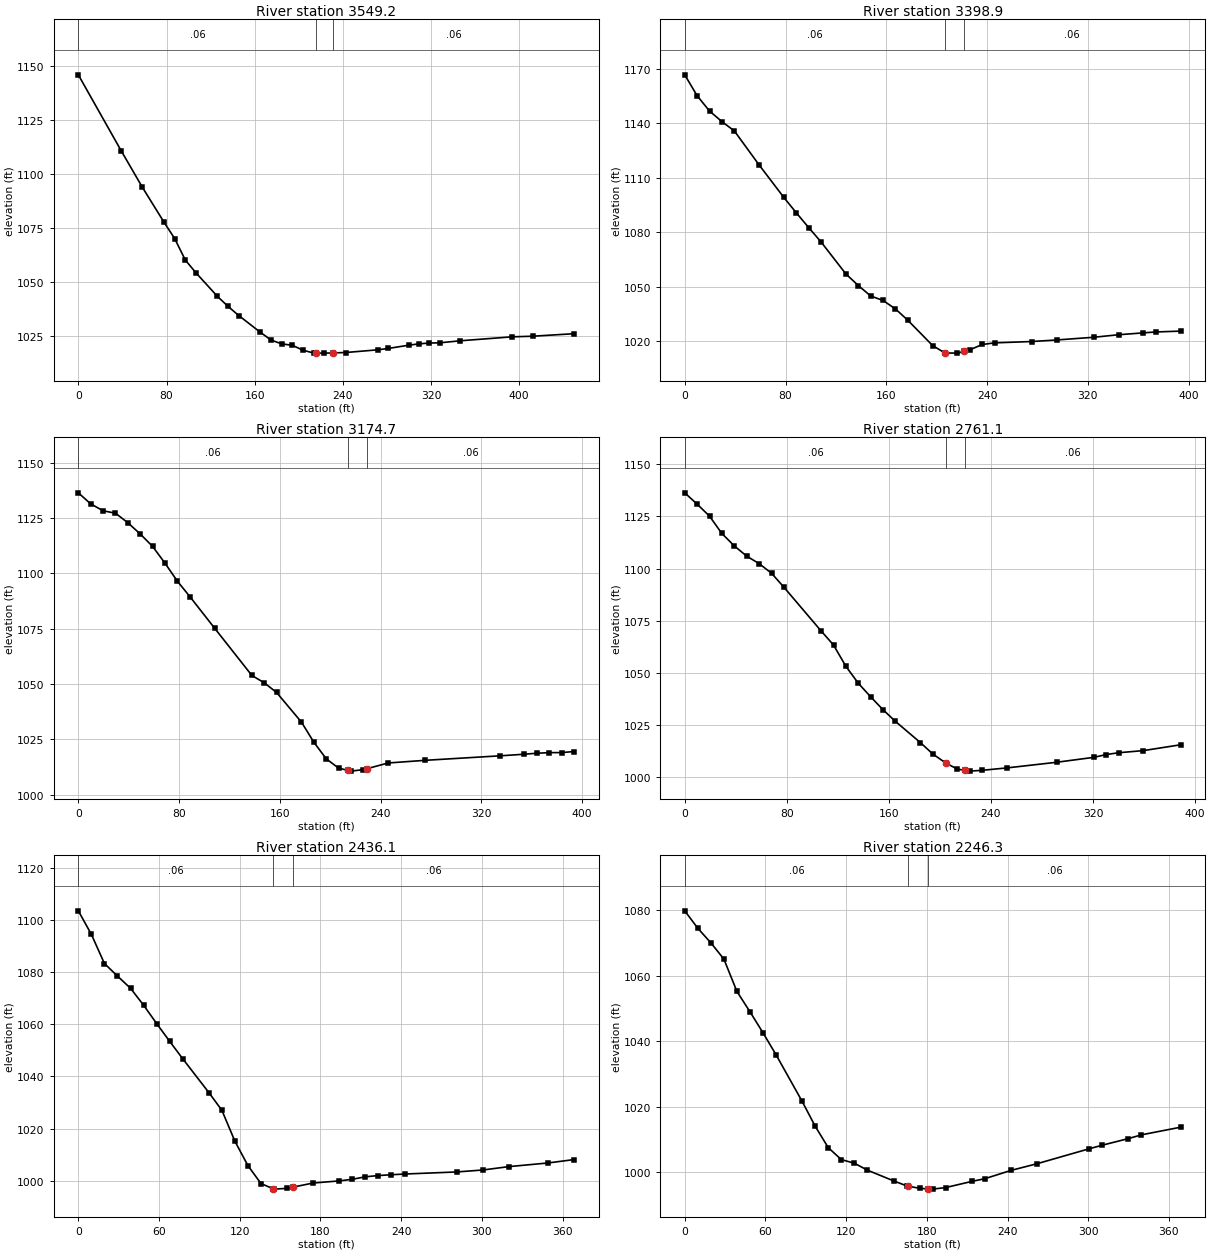
Type RM Length L Ch R = 1 ,3549.2  ,151.5,150.2,149
XS GIS Cut Line= 3
      1705777.49      337504.137     1705989.694      337350.237
     1706070.984      337181.035
#Sta/Elev= 30
       0 1145.69    38.8 1110.66    58.2 1093.63    77.7 1077.61    87.4 1070.03
    97.1 1060.06   106.8 1054.15   126.2 1043.29   135.9 1038.64   145.6 1034.43
     165 1026.77   174.8 1023.13   184.5 1021.36   194.2 1020.69   203.9 1018.41
   213.6 1017.12   215.9 1017.11   223.3 1017.08   230.9 1017.17   242.7 1017.37
   271.5  1018.6   280.9 1019.22   299.7 1020.74   309.1 1021.37   318.4 1021.75
   327.8 1021.84   346.6 1022.79   393.5 1024.61   412.3  1024.9   449.8 1026.06
#Mann= 3 , 0 , 0
       0     .06       0   215.9    .045       0   230.9     .06       0
Bank Sta=215.9,230.9
XS Rating Curve= 0 ,0
Exp/Cntr=0.3,0.1

Type RM Length L Ch R = 1 ,3398.9  ,224.1,224.3,224.5
XS GIS Cut Line= 2
     1705870.579      337631.965     1706173.317      337380.412
#Sta/Elev= 30
       0  1166.6     9.8 1155.12    19.7 1146.64    29.5 1140.87    39.4  1135.7
      59 1117.03    78.7 1099.08    88.6 1090.62    98.4 1082.51   108.2 1074.63
   127.9 1057.02   137.8 1050.62   147.6 1044.88   157.4 1042.41   167.3 1037.73
   177.1 1031.51   196.8 1017.57   206.6 1013.49   216.5 1013.42   221.6 1014.37
   226.3 1015.25   236.2 1018.17     246 1019.07   275.5 1019.81   295.2 1020.66
   324.7 1022.15   344.4 1023.54   364.1 1024.58   373.9 1025.06   393.6 1025.54
#Mann= 3 , 0 , 0
       0     .06       0   206.6    .045       0   221.6     .06       0
Bank Sta=206.6,221.6
XS Rating Curve= 0 ,0
Exp/Cntr=0.3,0.1

Type RM Length L Ch R = 1 ,3174.7  ,408.5,413.3,417.9
XS GIS Cut Line= 2
     1706017.509       337794.36     1706320.246      337542.808
#Sta/Elev= 30
       0 1136.38     9.8 1131.39    19.7 1128.26    29.5 1127.18    39.4 1122.82
    49.2 1117.75      59 1112.14    68.9 1104.51    78.7  1096.4    88.6 1089.45
   108.2 1075.21   137.8 1053.84   147.6 1050.55   157.4 1046.16   177.1  1032.8
     187 1023.69   196.8  1016.2   206.6    1012     214 1010.98   216.5 1010.63
   226.3 1011.31     229 1011.71     246 1014.31   275.5 1015.52   334.6 1017.54
   354.2 1018.27   364.1 1018.72   373.9 1018.98   383.8 1019.01   393.6 1019.49
#Mann= 3 , 0 , 0
       0     .06       0     214    .045       0     229     .06       0
Bank Sta=214,229
XS Rating Curve= 0 ,0
Exp/Cntr=0.3,0.1

Type RM Length L Ch R = 1 ,2761.1  ,323,324.3,325.7
XS GIS Cut Line= 2
     1706265.985      338061.598     1706608.656      337878.436
#Sta/Elev= 30
       0 1136.35     9.7 1130.91    19.4 1125.16    29.1 1116.82    38.9 1110.82
    48.6 1105.92    58.3 1102.35      68 1097.74    77.7 1091.03   106.8 1070.07
   116.6 1063.26   126.3 1053.02     136  1044.9   145.7 1038.39   155.4 1032.17
   165.1 1026.59   184.6 1016.43   194.3 1010.98   204.7 1006.51   213.7 1003.66
   219.7 1003.05   223.4 1002.68   233.1 1003.07   252.6 1004.23   291.4 1006.93
   320.6  1009.3   330.3 1010.63     340 1011.51   359.4 1012.53   388.6 1015.33
#Mann= 3 , 0 , 0
       0     .06       0   204.7    .045       0   219.7     .06       0
Bank Sta=204.7,219.7
XS Rating Curve= 0 ,0
Exp/Cntr=0.3,0.1

Type RM Length L Ch R = 1 ,2436.1  ,190.7,190.3,189.9
XS GIS Cut Line= 2
     1706492.929      338295.421     1706821.962       338129.37
#Sta/Elev= 30
       0 1103.66     9.7 1094.61    19.4 1083.41    29.1 1078.59    38.8  1073.9
    48.5 1067.42    58.2 1060.36    67.9 1053.52    77.6 1046.83      97 1033.85
   106.7 1027.04   116.4 1015.14   126.1 1005.74   135.8  998.86   144.8  996.87
   145.5  996.72   155.2  997.02   159.8  997.51   174.6  999.07     194  999.88
   203.7  1000.5   213.4 1001.46   223.1 1001.94   232.8 1002.25   242.5 1002.52
   281.3 1003.32   300.7 1004.07   320.1 1005.37   349.2 1006.77   368.6 1008.08
#Mann= 3 , 0 , 0
       0     .06       0   144.8    .045       0   159.8     .06       0
Bank Sta=144.8,159.8
XS Rating Curve= 0 ,0
Exp/Cntr=0.3,0.1

Type RM Length L Ch R = 1 ,2246.3  ,456.3,453.8,451.4
XS GIS Cut Line= 2
     1706582.104      338458.907     1706911.136      338292.856
#Sta/Elev= 30
       0 1079.73     9.7 1074.42    19.4 1069.98    29.1 1065.02    38.8 1055.15
    48.5 1048.95    58.2 1042.55    67.9 1035.84    87.3 1021.64      97 1014.06
   106.7 1007.55   116.4 1003.91   126.1 1002.81   135.8 1000.69   155.2  997.44
   164.9  995.92   166.1  995.82   174.6  995.15   181.1  994.99   184.3  994.91
     194  995.39   213.4  997.26   223.1  998.09   242.5 1000.61   261.9 1002.65
   300.7 1007.21   310.4  1008.3   329.8 1010.31   339.5 1011.45   368.6 1013.78
#Mann= 3 , 0 , 0
       0     .06       0   166.1    .045       0   181.1     .06       0
Bank Sta=166.1,181.1
XS Rating Curve= 0 ,0
Exp/Cntr=0.3,0.1

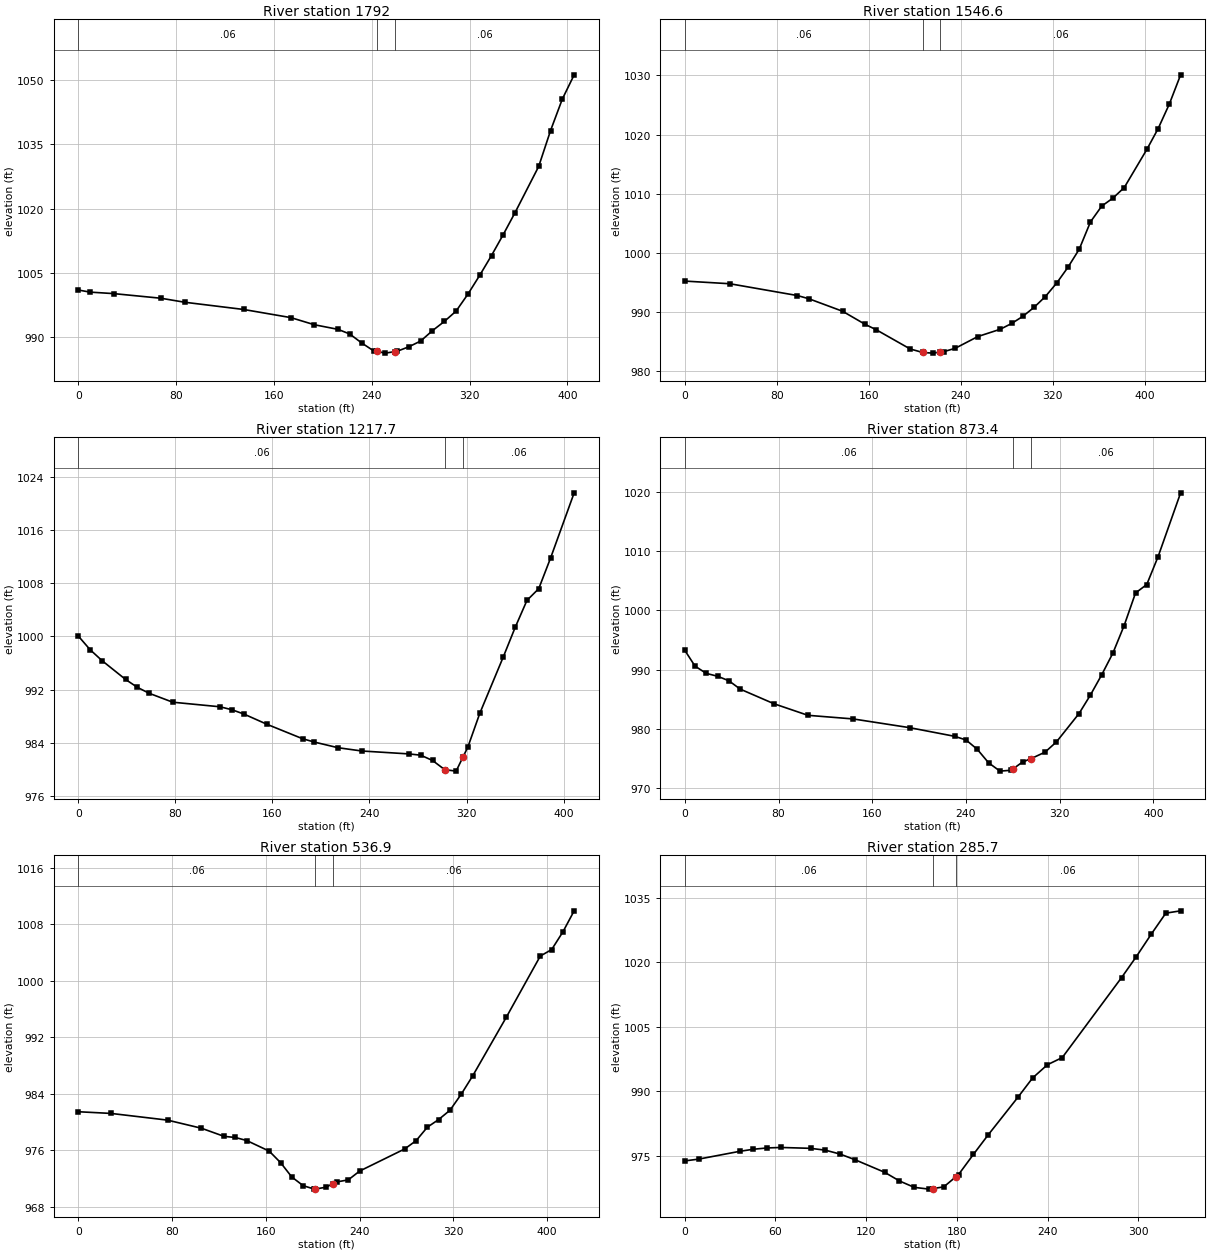
Type RM Length L Ch R = 1 ,1792    ,243.7,245.5,247.4
XS GIS Cut Line= 2
     1706860.416      338810.046     1707200.014      338588.519
#Sta/Elev= 30
       0 1000.98     9.6 1000.49      29 1000.14    67.6  999.06    86.9  998.13
   135.2  996.44   173.8  994.54   193.1  992.87   212.4   991.8     222  990.71
   231.7  988.63   241.4   986.8   243.9  986.66     251  986.25   258.9   986.6
   260.7  986.68   270.3  987.73     280  989.08   289.6  991.49   299.3  993.64
   308.9  996.05   318.6 1000.01   328.2 1004.38   337.9 1009.03   347.5 1013.92
   357.2 1019.07   376.5 1029.83   386.2  1038.2   395.8 1045.54   405.5 1051.21
#Mann= 3 , 0 , 0
       0     .06       0   243.9    .045       0   258.9     .06       0
Bank Sta=243.9,258.9
XS Rating Curve= 0 ,0
Exp/Cntr=0.3,0.1

Type RM Length L Ch R = 1 ,1546.6  ,338.1,328.8,319.5
XS GIS Cut Line= 2
     1706994.743      338988.199     1707374.474      338783.884
#Sta/Elev= 30
       0  995.24    39.2  994.79      98  992.79   107.8  992.26   137.2  990.14
   156.8  987.93   166.6     987     196  983.76     207  983.17   215.6  983.06
     222  983.23   225.4  983.32   235.2  983.88   254.8  985.86   274.4   987.1
   284.2  988.07     294  989.28   303.8  990.81   313.6  992.63   323.4   994.9
   333.2  997.57     343 1000.62   352.8 1005.25   362.6 1007.92   372.4 1009.28
   382.2 1011.06   401.8 1017.49   411.6    1021   421.4 1025.18   431.2 1030.11
#Mann= 3 , 0 , 0
       0     .06       0     207    .045       0     222     .06       0
Bank Sta=207,222
XS Rating Curve= 0 ,0
Exp/Cntr=0.3,0.1

Type RM Length L Ch R = 1 ,1217.7  ,346.3,344.2,342.2
XS GIS Cut Line= 2
     1707232.567      339353.588     1707484.809      339031.983
#Sta/Elev= 29
       0 1000.05     9.7     998    19.5  996.36    38.9  993.53    48.7  992.33
    58.4  991.44    77.8   990.1   116.8  989.41   126.5  988.97   136.2  988.34
   155.7  986.76   184.9   984.6   194.6   984.1   214.1  983.25   233.6  982.76
   272.5  982.32   282.2  982.13     292  981.33     302  979.95   311.4  979.73
     317  981.83   321.1  983.36   330.9  988.42   350.3  996.92   360.1 1001.36
   369.8 1005.42   379.5 1007.18   389.3 1011.81   408.7  1021.6
#Mann= 3 , 0 , 0
       0     .06       0     302    .045       0     317     .06       0
Bank Sta=302,317
XS Rating Curve= 0 ,0
Exp/Cntr=0.3,0.1

Type RM Length L Ch R = 1 ,873.4   ,336.4,336.4,336.5
XS GIS Cut Line= 3
     1707536.797       339564.35     1707541.521      339557.049
     1707766.742      339209.039
#Sta/Elev= 30
       0  993.27     8.7  990.61    18.3  989.38      28   988.9    37.6  988.14
    47.3  986.73    76.2  984.26   105.1  982.32   143.7  981.71   191.9  980.24
   230.4  978.78   240.1  978.16   249.7  976.58   259.3  974.32     269  972.92
   278.6  973.07   280.4  973.33   288.3  974.46   295.4  975.01   307.5  976.12
   317.2  977.84   336.5  982.62   346.1   985.7   355.7  989.09   365.4   992.8
     375  997.44   384.7 1002.92   394.3 1004.35     404 1009.06   423.2 1019.79
#Mann= 3 , 0 , 0
       0     .06       0   280.4    .045       0   295.4     .06       0
Bank Sta=280.4,295.4
XS Rating Curve= 0 ,0
Exp/Cntr=0.3,0.1

Type RM Length L Ch R = 1 ,536.9   ,258.5,251.2,243.9
XS GIS Cut Line= 3
     1707857.538      339680.619     1707862.263      339673.318
     1708087.484      339325.308
#Sta/Elev= 30
       0  981.44      28   981.2    76.2  980.25   105.1   979.1   124.4  977.95
     134  977.79   143.7  977.36   162.9  975.86   172.6  974.23   182.2  972.19
   191.9  970.96   201.5  970.47   202.3  970.49   211.1  970.73   217.3  971.22
   220.8   971.5   230.4  971.78   240.1  973.03   278.6  976.17   288.3  977.34
   297.9  979.25   307.5  980.33   317.2  981.65   326.8  983.92   336.5   986.5
   365.4  994.87   394.3 1003.51     404 1004.43   413.6 1006.94   423.2 1009.92
#Mann= 3 , 0 , 0
       0     .06       0   202.3    .045       0   217.3     .06       0
Bank Sta=202.3,217.3
XS Rating Curve= 0 ,0
Exp/Cntr=0.3,0.1

Type RM Length L Ch R = 1 ,285.7   ,265,254.9,243.9
XS GIS Cut Line= 3
     1708168.021      339745.929     1708183.757      339684.296
     1708249.173      339428.082
#Sta/Elev= 29
       0  973.85     9.1  974.26    36.4  976.08    45.4  976.56    54.5  976.86
    63.6  976.97    83.2  976.77      93  976.34   102.8  975.43   112.6  974.12
   132.2   971.2     142  969.19   151.8   967.7   161.6  967.29   164.1  967.42
   171.3  967.81   179.1  970.09   181.1  970.68   190.9  975.35   200.7   979.9
   220.3  988.61   230.1  993.13   239.9   996.2   249.7  997.86   288.9 1016.43
   298.7 1021.32   308.5  1026.5   318.2 1031.42     328 1031.96
#Mann= 3 , 0 , 0
       0     .06       0   164.1    .045       0   179.1     .06       0
Bank Sta=164.1,179.1
XS Rating Curve= 0 ,0
Exp/Cntr=0.3,0.1

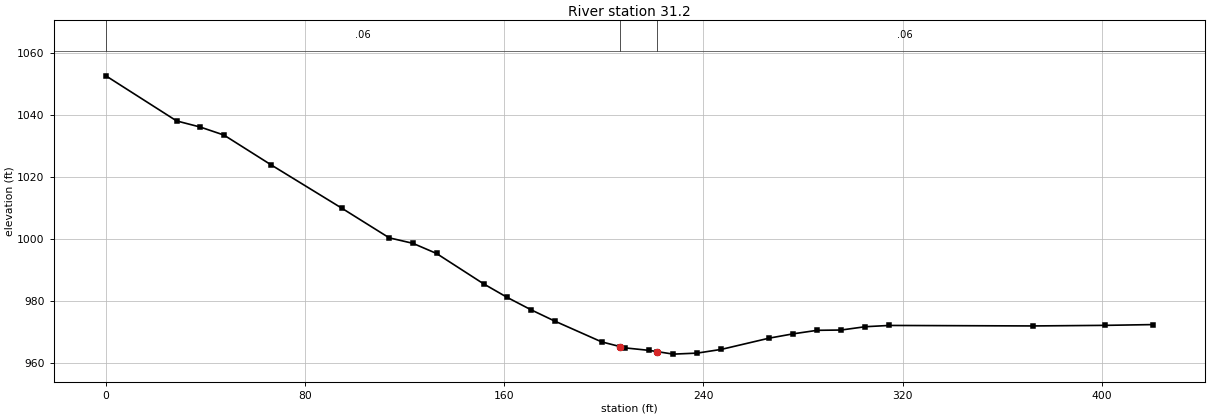
Type RM Length L Ch R = 1 ,31.2    ,24.2,30.9,38.3
XS GIS Cut Line= 3
     1708412.436      339406.724     1708461.216      339609.552
      1708501.87      339817.631
#Sta/Elev= 30
       0 1052.69    28.4 1038.13    37.9 1036.15    47.4 1033.57    66.4 1023.92
    94.8 1009.93   113.8 1000.38   123.3  998.61   132.8  995.33   151.7  985.53
   161.2  981.14   170.7  977.17   180.2  973.53   199.1  966.79   206.4  965.29
   208.6  964.84   218.2  964.04   221.4  963.64   227.9  962.83   237.5  963.16
   247.2  964.36   266.4  967.99   276.1  969.39   285.7  970.52   295.3  970.61
     305  971.68   314.6  972.09   372.4  971.93   401.4  972.12   420.6  972.37
#Mann= 3 , 0 , 0
       0     .06       0   206.4    .045       0   221.4     .06       0
Bank Sta=206.4,221.4
XS Rating Curve= 0 ,0
Exp/Cntr=0.3,0.1

Chan Stop Cuts=-1
Use User Specified Reach Order=0
Composite Channel Slope=5